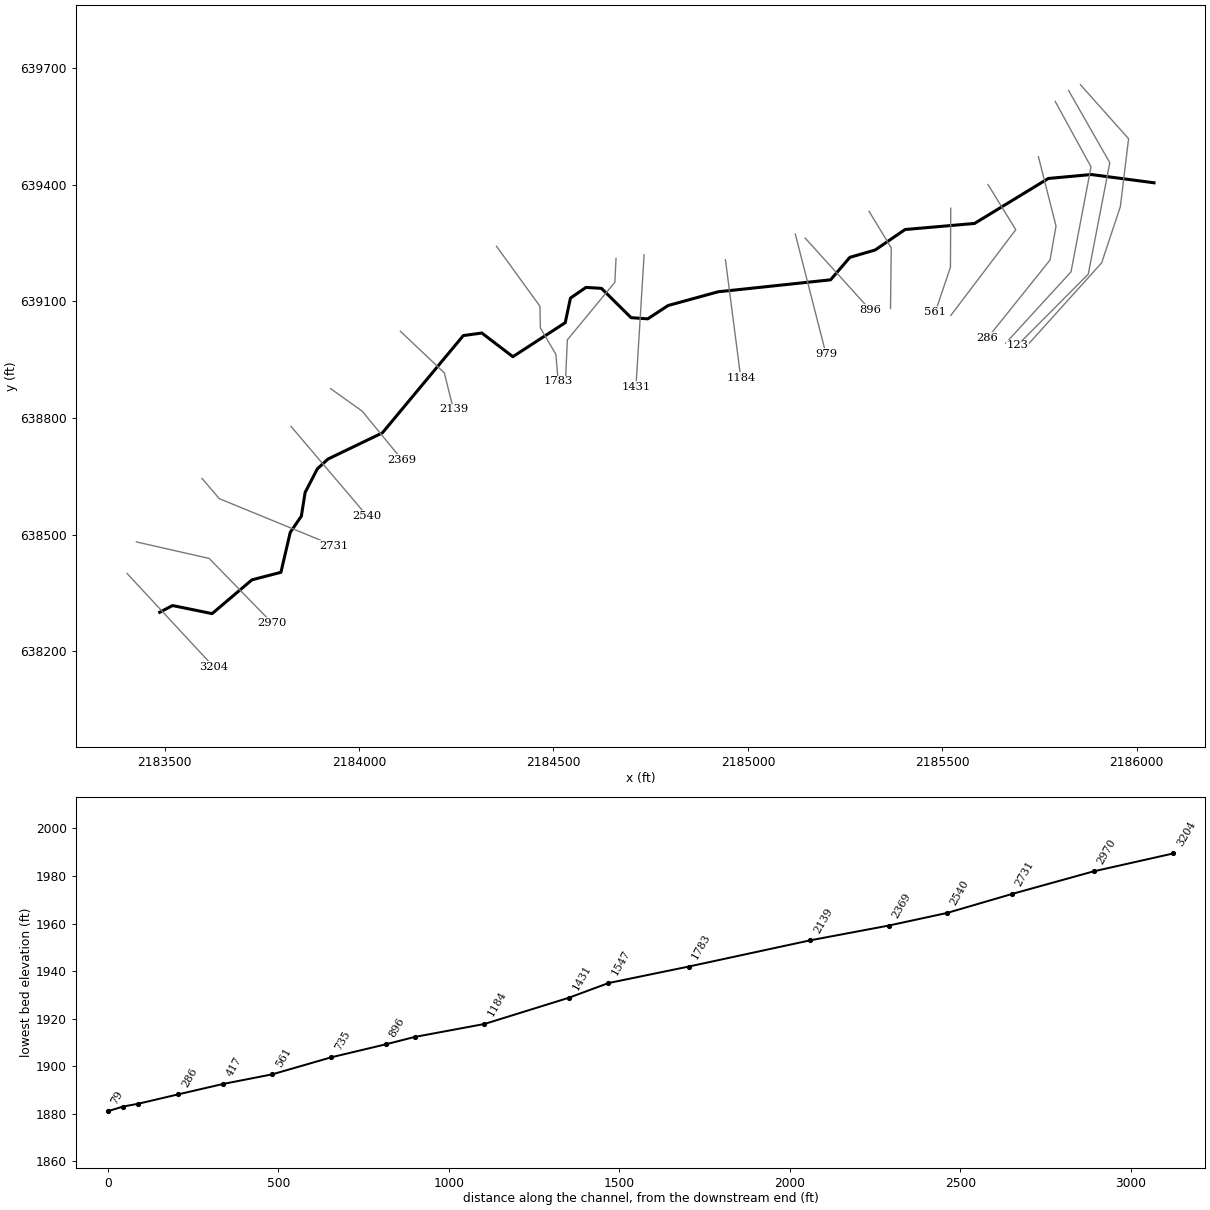
--- BENSRN.prj (project) ---

Proj Title=BENSRN
Current Plan=p01
Default Exp/Contr=0,0
English Units
Geom File=g01
Flow File=f01
Plan File=p01
BEGIN DESCRIPTION:
---------- MODELED AS PART OF WVEMD CTP PROGRAM, 2023----------
Stream Name: Bens Run
Flood Zone:  AFH
Upshur County, WV
HEC-RAS Version: RAS 6.3
Vertical Datum: NAVD88
Projection: NAD 1983 StatePlane West Virginia S FIPS 4702 (US Feet)
Terrain: 1-meter LIDAR (FEMA Region III 3DEP collected 2016-2018)
Land Use: 2019 NLCD
Hydrologic Method:
WV 2010 Regional Regression Equations
Additional Model Notes:
None
END DESCRIPTION:
DSS Export Rating Curves= 0
DSS Export Rating Curve Sorted= 0
DSS Export Volume Flow Curves= 0
DXF OffsetX= 0
DXF OffsetY= 0
DXF ScaleX= 0
DXF ScaleY= 0

--- BENSRN.p01 (plan) ---

Plan Title=Floodplain
Program Version=4.00
Geom File=g01
Flow File=f01
K Sum by GR=0
Std Step Tol=0.01
Critical Tol=0.01
Num of Std Step Trials=20
Max Error Tol=0.3
Flow Tol Ratio=0.001
Split Flow NTrial=30
Split Flow Tol=0.02
Split Flow Ratio=0.02
Log Output Level=0
Friction Slope Method=1
Unsteady Friction Slope Method=2
Unsteady Bridges Friction Slope Method=1
Global Log Level=0
CheckData=False
Run HTab=0
Run UNet=0
Run PostProcess=0
UNET Theta=0
UNET Theta Warmup=0
UNET ZTol=0
UNET ZSATol=0
UNET MxIter=0
UNET MaxInSteps=0
UNET DtIC=0
UNET DtMin=0
UNET MaxCRTS=0
UNET WFStab=0
UNET SFStab=0
UNET WFX=0
UNET SFX=0
UNET DSS MLevel=0
UNET DZMax Abort=0
UNET Convert EG Bridges=0
UNET Use Existing IB Tables=0
UNET Froude Limit=0
UNET Froude Power=0
Write IC File=0
Echo Input=False
Echo Output=False
Write Detailed=0

--- BENSRN.f01 (steady flow) ---

Flow Title=Flows
Program Version=6.31
Number of Profiles= 1
Profile Names=01pct
River Rch & RM=BENSRN,Main,3204
     333
River Rch & RM=BENSRN,Main,1783
     420
Boundary for River Rch & Prof#=BENSRN,Main            , 1
Up Type= 0
Dn Type= 3
Dn Slope=0.04435
DSS Import GetInterval= 0
DSS Import GetPeak= 0
DSS Import FillOption= 0

--- BENSRN.g01 (geometry) ---

Geom Title=Geometry
Program Version=6.31

River Reach=BENSRN          ,Main
Reach XY= 30
     2183487.365      638300.687     2183520.273         638318.
      2183622.09      638297.196     2183724.623      638384.104
     2183799.083      638403.449     2183822.978      638505.981
     2183851.623      638547.904     2183861.266      638608.685
     2183892.716      638669.524     2183919.987      638694.677
     2184059.921      638761.983     2184268.105      639012.262
     2184315.752      639018.815     2184395.563      638957.948
     2184530.174      639045.343     2184543.653      639108.642
     2184583.515      639136.114     2184623.378      639133.682
     2184699.612      639058.277     2184742.422      639055.301
     2184794.676      639089.498     2184923.163       639124.81
     2185212.618       639155.63      2185262.21      639213.435
     2185327.284      639232.322     2185404.233      639284.976
     2185582.857      639300.601     2185772.555      639416.268
     2185883.043      639426.427     2186044.525      639405.137

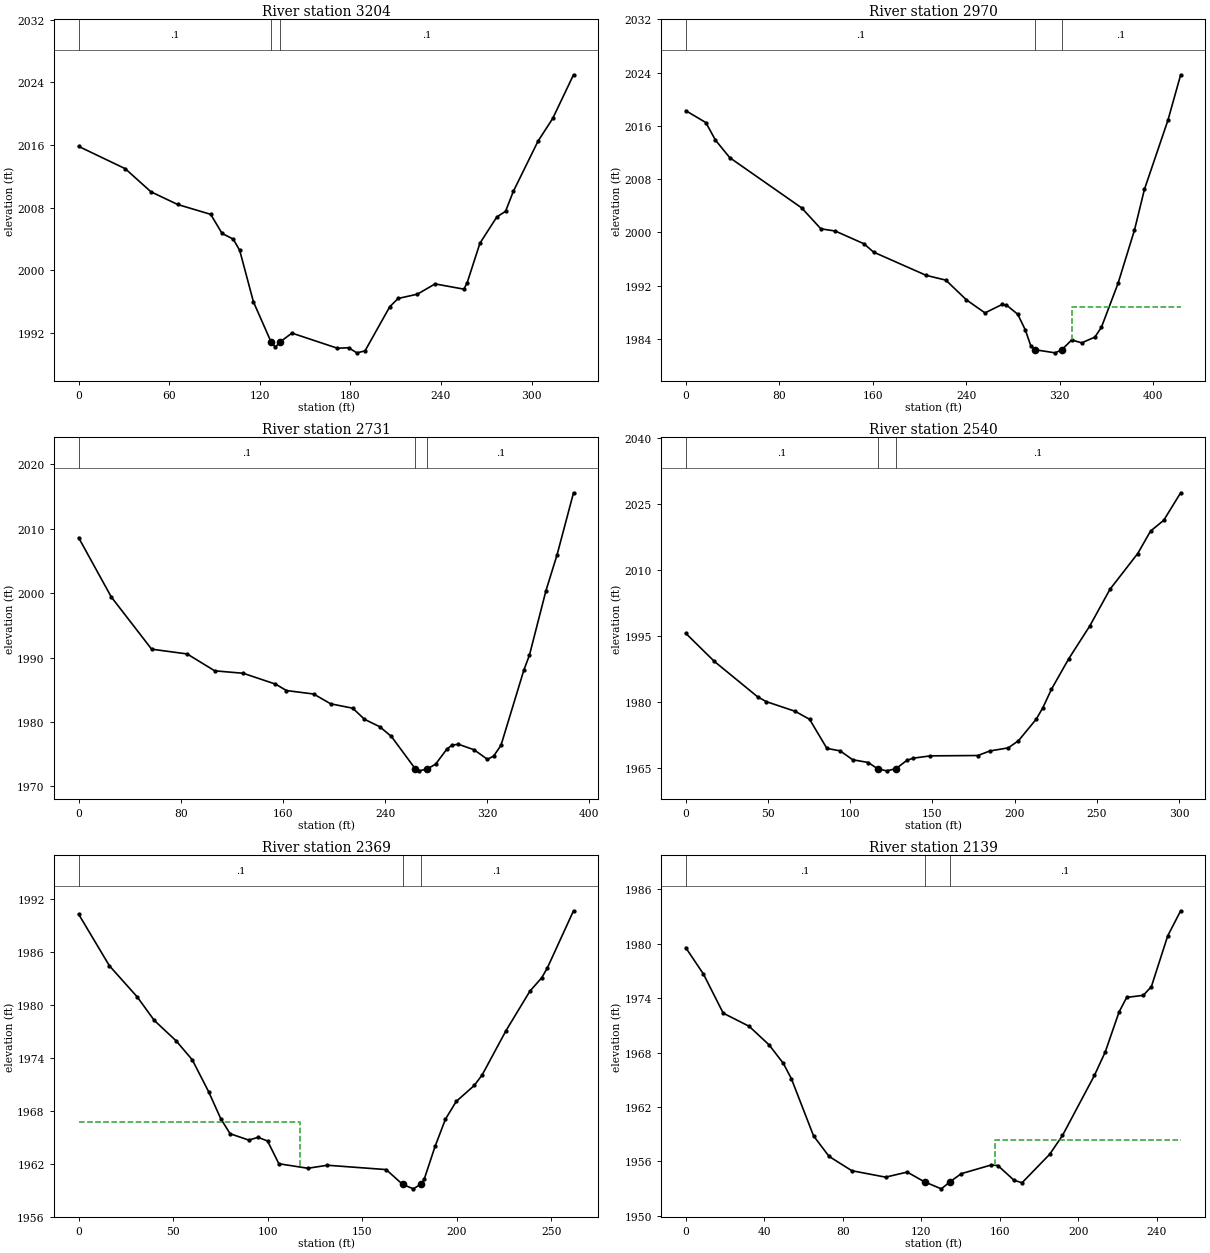
Type RM Length L Ch R = 1 ,3204    ,234.3,234.3,234.3
XS GIS Cut Line= 2
2183403.58691189638400.2826381722183626.53226133638159.932633193
#Sta/Elev= 30
       0 2015.83    30.9 2012.98    47.9 2010.03    65.6 2008.41    87.5 2007.15
      95 2004.72   102.4 2003.99   106.7 2002.55   115.8 1995.98  127.41 1990.89
   130.3  1990.2   133.7  1990.9   141.3 1991.99   171.4 1990.06   178.8 1990.12
   184.3 1989.47   189.7 1989.72   206.1 1995.36   211.6 1996.41   224.4 1996.96
   236.1 1998.27   255.2  1997.6   257.4 1998.45   265.8 2003.46     277 2006.82
   282.8 2007.54   287.9 2010.07   304.3  2016.5     314 2019.39   327.8 2024.97
#Mann= 3 ,-1,0
       0      .1       0  127.41    .045       0   133.7      .1       0
Bank Sta=127.41,133.7
XS Rating Curve= 0 ,0
Exp/Cntr(USF)=0,0
Exp/Cntr=0.3,0.1

Type RM Length L Ch R = 1 ,2970    ,233.3,238.9,242
XS GIS Cut Line= 3
2183427.41861797638481.5792194162183614.48918105638439.133594702
2183776.15499964638273.374970579
#Sta/Elev= 30
       0  2018.3    17.2 2016.51    25.4 2013.88    37.7 2011.23    99.2 2003.69
   115.6 2000.55   127.9 2000.22   152.5  1998.3   160.7 1997.05   205.7 1993.56
   222.5 1992.84   240.1 1989.88     256 1987.92   270.8  1989.2   274.4 1989.09
     284 1987.72   290.6 1985.32   295.1 1983.01  298.871982.384     316 1981.92
   321.7 1982.38   330.2 1983.86   338.7 1983.42     350 1984.28   355.6 1985.76
   369.8 1992.34   383.9 2000.37   392.4 2006.48   412.5 2016.86   423.4 2023.69
#Mann= 3 ,-1,0
       0      .1       0  298.87    .045       0   321.7      .1       0
#XS Ineff= 2 , 0
                          330.03         1988.78
Permanent Ineff=
       F       F
Bank Sta=298.87,321.7
XS Rating Curve= 0 ,0
Exp/Cntr(USF)=0,0
Exp/Cntr=0.3,0.1

Type RM Length L Ch R = 1 ,2731    ,195.7,190.2,185.8
XS GIS Cut Line= 3
2183596.32419846638644.6707516232183640.53660392638592.879076657
 2183936.1281147638471.610764541
#Sta/Elev= 30
       0 2008.62    25.6 1999.41    57.2 1991.31      85 1990.57   106.6 1987.95
   128.9 1987.57   154.2 1985.89   162.8 1984.89   184.1 1984.35   197.4 1982.83
   214.7 1982.15   223.9 1980.43   235.9 1979.27     245 1977.76  263.771972.714
   266.6 1972.43     273 1972.72   279.6 1973.47   288.2 1975.75   292.5 1976.43
   297.5 1976.55   309.7  1975.7   320.2 1974.21   325.1 1974.73   330.8  1976.4
   348.7 1988.06   353.1  1990.4     366 2000.38   374.7 2005.95   387.6 2015.58
#Mann= 3 ,-1,0
       0      .1       0  263.77    .045       0     273      .1       0
Bank Sta=263.77,273
XS Rating Curve= 0 ,0
Exp/Cntr(USF)=0,0
Exp/Cntr=0.3,0.1

Type RM Length L Ch R = 1 ,2540    ,172.1,171.6,171.4
XS GIS Cut Line= 2
2183825.10585211638778.5399891752184020.04591145638549.290479388
#Sta/Elev= 30
       0  1995.7    17.3 1989.34    43.8 1981.24      49 1980.17    66.5 1977.98
    75.3 1976.16    85.8 1969.56    93.9 1968.99   101.5 1966.98     111 1966.35
   116.6 1964.93   122.1 1964.46   127.8 1964.94   134.4 1966.83   138.3 1967.34
   148.8 1967.86   177.6 1967.94   184.8 1968.96   196.1 1969.68   202.3  1971.3
   213.1  1976.2   217.1 1978.78   222.3 1982.96   232.8 1989.88   245.6 1997.33
   257.9 2005.68   274.8 2013.81   282.6 2018.91   290.6 2021.35   300.9  2027.6
#Mann= 3 ,-1,0
       0      .1       0   116.6    .045       0   127.8      .1       0
Bank Sta=116.6,127.8
XS Rating Curve= 0 ,0
Exp/Cntr(USF)=0,0
Exp/Cntr=0.3,0.1

Type RM Length L Ch R = 1 ,2369    ,228,229.5,230.3
XS GIS Cut Line= 3
2183926.88977099638875.7015777252184007.94228055638817.980705626
2184110.83053006638692.607724256
#Sta/Elev= 30
       0 1990.24    16.3 1984.39      31 1980.87      40 1978.21    51.5 1975.91
    60.1 1973.75    68.7 1970.16    75.2 1967.07    80.1 1965.38      90 1964.66
    94.9 1964.97    99.9 1964.56   105.9 1961.98   121.2 1961.47   131.6 1961.81
   162.6 1961.32   171.3 1959.65     177 1959.14  180.84 1959.65   182.7  1960.2
   188.5 1963.95     194 1967.04   199.7 1969.04   209.2 1970.84   213.4 1972.04
     226 1977.05   238.6 1981.51   244.9 1983.04   247.9 1984.17   261.7 1990.62
#Mann= 3 ,-1,0
       0      .1       0   171.3    .045       0  180.84      .1       0
#XS Ineff= 2 , 0
          117.05 1966.76
Permanent Ineff=
       F       F
Bank Sta=171.3,180.84
XS Rating Curve= 0 ,0
Exp/Cntr(USF)=0,0
Exp/Cntr=0.3,0.1

Type RM Length L Ch R = 1 ,2139    ,360.3,356.7,353.6
XS GIS Cut Line= 3
2184106.27111408 639023.351488462184219.30199993638916.357235095
2184242.59101177638822.756669247
#Sta/Elev= 30
       0 1979.58       9 1976.67    19.1 1972.35    32.3  1970.9    42.5 1968.84
    49.7 1966.81    53.8 1965.12    65.1 1958.81      73 1956.54    84.6 1954.96
   101.8 1954.25   112.8 1954.81  121.63 1953.73   130.2 1952.96  134.57 1953.73
   140.3 1954.63   155.7  1955.6     159 1955.53   167.2 1953.91   171.3 1953.63
   185.4 1956.78   191.9 1958.85   208.2 1965.49   213.7 1968.08   220.7 1972.47
   224.6 1974.09   233.1 1974.32   237.2 1975.29   245.5 1980.88   252.1 1983.65
#Mann= 3 ,-1,0
       0      .1       0  121.63    .045       0  134.57      .1       0
#XS Ineff= 2 , 0
                          157.43         1958.36
Permanent Ineff=
       F       F
Bank Sta=121.63,134.57
XS Rating Curve= 0 ,0
Exp/Cntr(USF)=0,0
Exp/Cntr=0.3,0.1

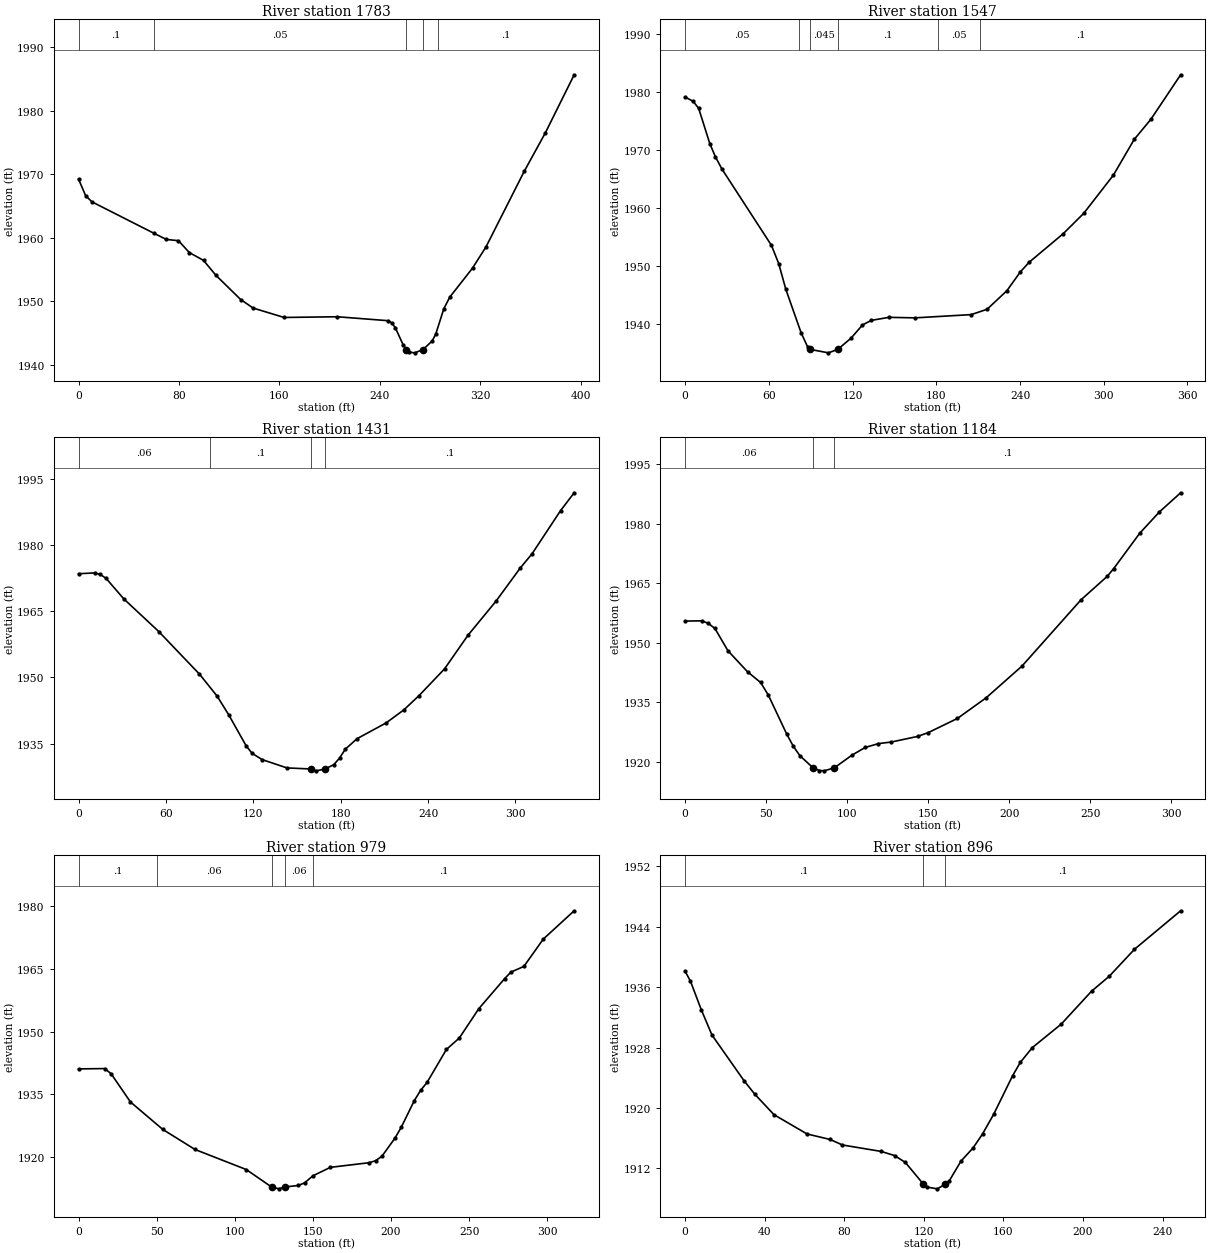
Type RM Length L Ch R = 1 ,1783    ,251.2,235.5,212.2
XS GIS Cut Line= 5
2184353.50009972639241.7417405472184465.20691528639087.649898875
2184466.25224079639031.8586870712184506.06502522 638964.26954142
2184512.12129465638894.337041522
#Sta/Elev= 30
       0 1969.19     5.6 1966.61    10.6 1965.65      60 1960.71    69.9 1959.74
    79.5 1959.55    88.2 1957.68    99.5 1956.45   109.4  1954.1   129.1  1950.3
     139 1948.96   163.7 1947.48   206.1 1947.59   246.1 1946.98   249.5 1946.63
   252.4 1945.83   258.5  1943.2   261.2 1942.44   263.2 1942.03   267.8 1941.92
  274.39 1942.44   281.7 1943.79   284.5 1944.86     291 1948.87   295.7 1950.68
   313.8 1955.23   324.6 1958.59   355.2 1970.52   371.8 1976.48   394.8 1985.62
#Mann= 5 ,-1,0
       0      .1       0      60     .05       0   261.2    .045       0
  274.39     .05       0  286.12      .1       0
Bank Sta=261.2,274.39
XS Rating Curve= 0 ,0
Exp/Cntr(USF)=0,0
Exp/Cntr=0.3,0.1

Type RM Length L Ch R = 1 ,1547    ,108.1,116,120.3
XS GIS Cut Line= 4
2184660.85099525 639210.896313262184657.90913326639149.445282931
2184535.69314386639001.3046897222184531.12686308 638899.87264769
#Sta/Elev= 30
       0 1979.14     5.7 1978.42     9.7 1977.21    17.7 1971.11    21.7 1968.84
    26.3 1966.75    61.9 1953.53    67.1 1950.38    72.2 1945.93    83.1 1938.47
    87.8    1936   89.48 1935.58   102.7 1934.98109.4294 1935.58   118.9 1937.51
   127.1 1939.79   133.4 1940.58     146 1941.11   164.8 1941.02     205 1941.58
   216.4  1942.5   230.6 1945.71   240.2 1948.94   246.5 1950.61     271 1955.56
   285.7 1959.08   306.9 1965.66   321.8 1971.82   333.8 1975.31   355.1 1982.99
#Mann= 6 ,-1,0
       0     .05       0   81.52      .1       0   89.48    .045       0
109.4294      .1       0  181.52     .05       0  211.52      .1       0
Bank Sta=89.48,109.4294
XS Rating Curve= 0 ,0
Exp/Cntr(USF)=0,0
Exp/Cntr=0.3,0.1

Type RM Length L Ch R = 1 ,1431    ,244.2,247.4,247.4
XS GIS Cut Line= 2
2184733.09319085639220.0289155742184712.03966444638880.365356175
#Sta/Elev= 30
       0 1973.49    10.9 1973.66    14.9 1973.31    18.9 1972.42    30.9 1967.82
      55 1960.39      83 1950.72      95 1945.79     103 1941.55   115.1 1934.44
   119.1 1932.79     126 1931.36   143.1 1929.47   159.71929.228   163.2 1928.81
  169.04 1929.22   175.2 1930.19   179.2 1931.71   183.2 1933.74   191.2  1936.1
   211.1 1939.66   223.3 1942.62   233.8 1945.87   251.3 1951.93   267.4 1959.55
   286.6 1967.26   303.4 1974.83   311.4 1978.01     331 1987.81   340.3 1991.83
#Mann= 4 ,-1,0
       0     .06       0      90      .1       0   159.7    .045       0
  169.04      .1       0
Bank Sta=159.7,169.04
XS Rating Curve= 0 ,0
Exp/Cntr(USF)=0,0
Exp/Cntr=0.3,0.1

Type RM Length L Ch R = 1 ,1184    ,203.1,204.9,205.6
XS GIS Cut Line= 2
2184942.22488651639207.3967997282184981.52480248638904.226019438
#Sta/Elev= 30
       0 1955.49    10.3 1955.55    14.3 1954.92    18.4 1953.63    26.4 1948.04
    38.5 1942.73    46.6 1940.03    51.3 1936.89    62.7 1927.04    66.8 1923.95
    70.8 1921.61    78.9 1918.56    82.9 1917.87    85.8 1917.79   92.09 1918.56
   103.1 1921.78   111.1 1923.67   119.2 1924.64   127.3 1925.05   143.4 1926.45
   150.1 1927.43     168 1930.98   185.7 1936.17   207.9 1944.19   244.2 1960.83
   260.4 1966.75   264.4  1968.7   280.5 1977.62   292.6 1982.97   305.7 1987.79
#Mann= 3 ,-1,0
       0     .06       0    78.9    .045       0   92.09      .1       0
Bank Sta=78.9,92.09
XS Rating Curve= 0 ,0
Exp/Cntr(USF)=0,0
Exp/Cntr=0.3,0.1

Type RM Length L Ch R = 1 ,979     ,78.3,83.3,88.4
XS GIS Cut Line= 2
 2185121.8816452 639273.364515812185200.48147713638965.983030238
#Sta/Elev= 30
       0 1941.06    16.7 1941.14    20.8  1939.9    33.2 1933.13    53.9 1926.56
    74.5 1921.76   107.3 1916.96  123.571912.767   128.2 1912.33  132.111912.778
   140.6 1913.13   144.7 1913.76     150 1915.45   161.2 1917.48     186 1918.59
   190.1 1919.06   194.2 1920.13   202.6  1924.5   206.6  1927.1   214.9 1933.44
     219 1935.93   223.1 1937.82   235.5 1945.72   243.8 1948.48   256.2 1955.47
   272.7 1962.65   276.8 1964.25   285.1 1965.61   297.5 1972.15   317.3 1978.94
#Mann= 5 ,-1,0
       0      .1       0      50     .06       0  123.57    .045       0
  132.11     .06       0     150      .1       0
Bank Sta=123.57,132.11
XS Rating Curve= 0 ,0
Exp/Cntr(USF)=0,0
Exp/Cntr=0.3,0.1

Type RM Length L Ch R = 1 ,896     ,161.9,160.6,157.7
XS GIS Cut Line= 2
2185147.05473797639263.1945258712185314.28160286639078.554430285
#Sta/Elev= 30
       0 1938.11     2.7 1936.79     8.1 1933.03    13.5 1929.66    29.7 1923.58
    35.1  1921.8    44.7  1919.1    61.3 1916.55    72.9 1915.82    79.1 1915.09
    98.5 1914.24   105.3 1913.69   110.7 1912.78119.7688 1909.91   121.4 1909.52
   126.8 1909.28  130.83 1909.91   132.8 1910.34   138.7 1912.96   144.7 1914.68
   149.5 1916.54   155.1 1919.15   164.6 1924.25   168.5 1926.03   174.5 1927.98
   189.1 1931.11   204.3 1935.46   213.2 1937.44   225.9 1941.02   249.1 1946.12
#Mann= 3 ,-1,0
       0      .1       0119.7688    .045       0  130.83      .1       0
Bank Sta=119.7688,130.83
XS Rating Curve= 0 ,0
Exp/Cntr(USF)=0,0
Exp/Cntr=0.3,0.1

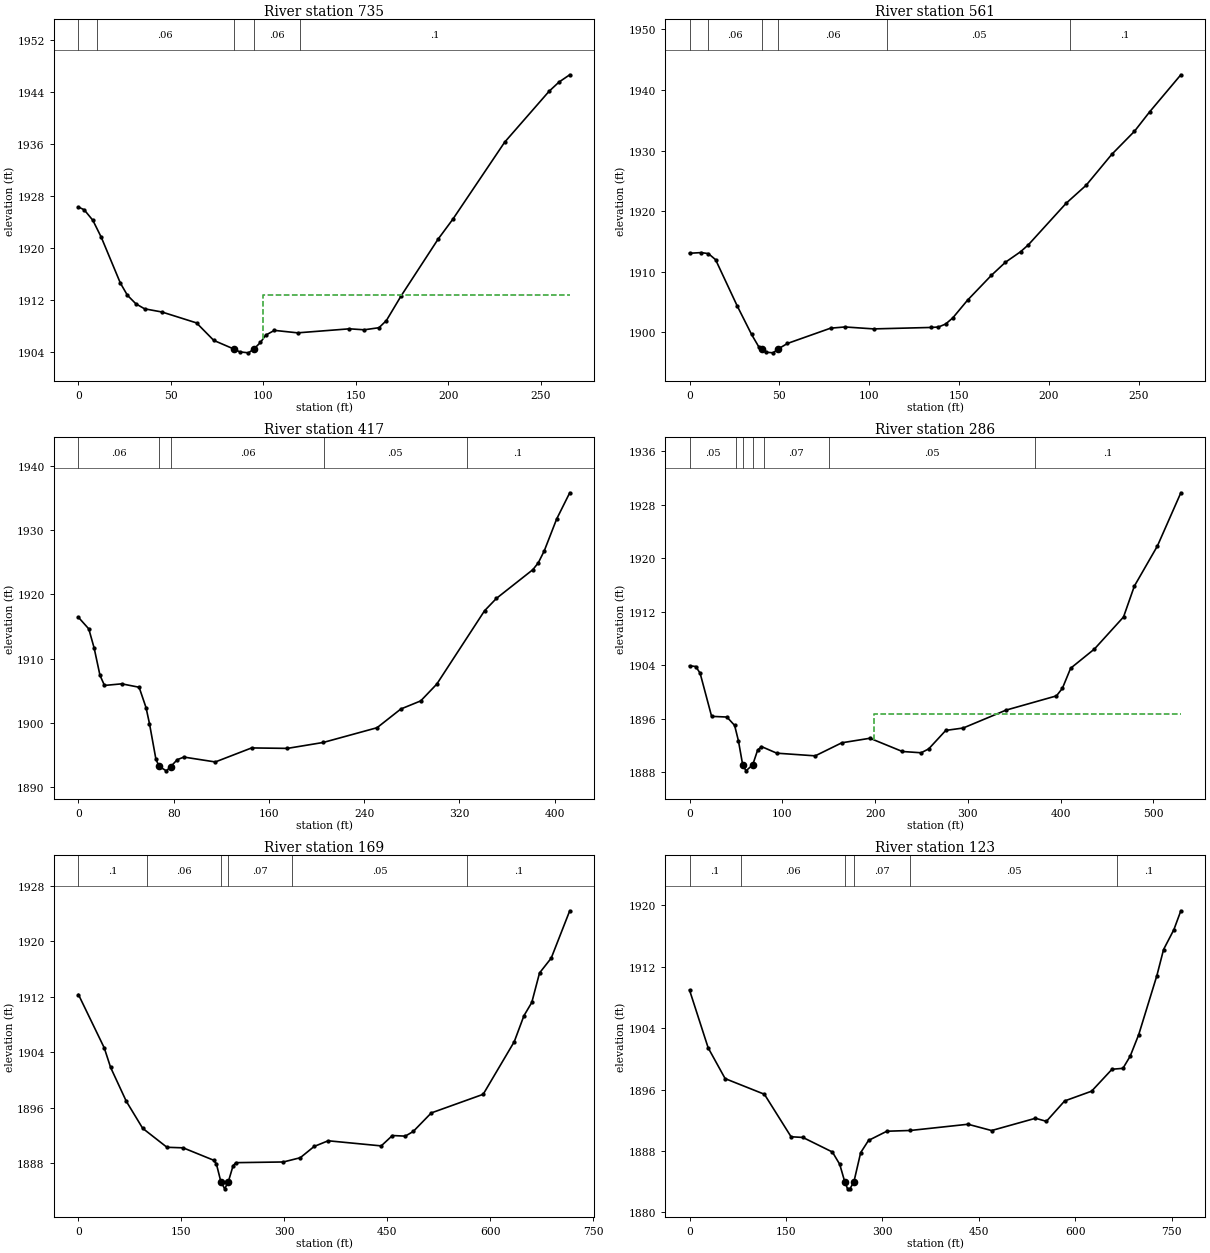
Type RM Length L Ch R = 1 ,735     ,178.7,173.7,167.6
XS GIS Cut Line= 3
2185311.55527689639331.8060862782185368.63921337639237.699201669
2185366.69787201639081.982278747
#Sta/Elev= 30
       0 1926.26     3.1 1925.84     7.8 1924.22    12.4 1921.58    22.7 1914.54
    26.5 1912.67    31.1 1911.35    35.8 1910.58    45.2 1910.09    63.9 1908.41
    73.2 1905.72    83.9 1904.41    87.3 1903.95      92  1903.8   94.99 1904.41
    98.5 1905.41   101.3 1906.52     106 1907.26   118.6 1906.88   146.6  1907.5
   154.6 1907.35   162.6 1907.67   166.6 1908.77   174.6 1912.58   194.6 1921.32
   202.6  1924.4   230.6 1936.25   254.6 1944.08     260 1945.51   265.8 1946.63
#Mann= 5 ,-1,0
       0      .1       0      10     .06       0    83.9    .045       0
   94.99     .06       0  120.07      .1       0
#XS Ineff= 2 , 0
                           99.72         1912.77
Permanent Ineff=
       F       F
Bank Sta=83.9,94.99
XS Rating Curve= 0 ,0
Exp/Cntr(USF)=0,0
Exp/Cntr=0.3,0.1

Type RM Length L Ch R = 1 ,561     ,139.5,144.4,150.2
XS GIS Cut Line= 3
2185521.63141101639339.6940000932185520.88144926639188.201725963
2185481.88343809639072.707615983
#Sta/Elev= 30
       0 1913.05     6.5 1913.16    10.5 1912.99    14.5 1911.99    26.5 1904.38
    34.5 1899.67    38.5 1897.63   40.21 1897.26    42.5 1896.73    46.5 1896.62
    49.3 1897.26    54.5 1898.17    78.5 1900.69    86.5 1900.89   102.5 1900.57
   134.5 1900.81   138.5 1900.88   142.5 1901.37   146.5 1902.39   154.7 1905.31
   167.9 1909.39   175.8 1911.57   184.2  1913.3   188.5 1914.43   209.6 1921.31
   220.7 1924.27   234.9 1929.35   247.6 1933.18     256 1936.37   273.4  1942.5
#Mann= 6 ,-1,0
       0      .1       0      10     .06       0   40.21    .045       0
    49.3     .06       0     110     .05       0  211.49      .1       0
Bank Sta=40.21,49.3
XS Rating Curve= 0 ,0
Exp/Cntr(USF)=0,0
Exp/Cntr=0.3,0.1

Type RM Length L Ch R = 1 ,417     ,133.3,130.6,126.8
XS GIS Cut Line= 3
2185617.48867471639400.6274686792185688.84532085639284.497376069
2185521.86580177639064.107902557
#Sta/Elev= 30
       0 1916.43     8.7 1914.63    13.2 1911.66    18.1 1907.42    21.9 1905.84
    36.4 1906.09      51 1905.56    56.8  1902.4    59.7 1899.91    65.1 1894.39
67.799311893.256    73.9 1892.5777.619211893.242      83  1894.3    88.6 1894.71
     115 1893.95   145.5 1896.13   175.6 1896.06   205.7 1896.98   250.9 1899.27
   270.9 1902.18   287.6 1903.44   301.1 1906.05   341.2 1917.44   351.2 1919.37
   381.8 1923.83   386.4  1924.9   391.4 1926.76   401.8  1931.7   412.8 1935.78
#Mann= 5 ,-1,0
       0     .06       067.79931    .045       077.61921     .06       0
   206.3     .05       0   326.3      .1       0
Bank Sta=67.79931,77.61921
XS Rating Curve= 0 ,0
Exp/Cntr(USF)=0,0
Exp/Cntr=0.3,0.1

Type RM Length L Ch R = 1 ,286     ,121.5,117.5,112.4
XS GIS Cut Line= 4
2185747.09418329639472.2515655222185792.36760389639293.946333153
2185776.98787267639206.5298485242185616.35178429639006.126490826
#Sta/Elev= 30
       0 1903.93     6.7 1903.82    11.4 1902.82    23.8 1896.37    40.3 1896.27
    48.6 1895.02    52.7 1892.72   57.28 1889.14    60.9 1888.23   68.13 1889.14
    73.3 1891.29    77.5 1891.86      94 1890.87   135.5 1890.47   164.1 1892.42
   194.5  1893.1   229.4 1891.12   249.7 1890.93   257.8 1891.51   276.2 1894.27
     295 1894.63   341.1  1897.3   395.5 1899.43   401.9 1900.56   410.8 1903.56
   436.5 1906.44   467.8 1911.22   479.5 1915.84   504.3 1921.82   529.6 1929.78
#Mann= 7 ,-1,0
       0     .05       0      50     .06       0   57.28    .045       0
   68.13     .06       0      80     .07       0     150     .05       0
  372.72      .1       0
#XS Ineff= 2 , 0
                          198.68         1896.76
Permanent Ineff=
       F       F
Bank Sta=57.28,68.13
XS Rating Curve= 0 ,0
Exp/Cntr(USF)=0,0
Exp/Cntr=0.3,0.1

Type RM Length L Ch R = 1 ,169     ,46,45.8,45.6
XS GIS Cut Line= 4
2185790.29601948639614.3628687832185882.38414399639446.103085722
2185830.92047523639176.1239313572185662.74430992638992.374137107
#Sta/Elev= 30
       0 1912.34    37.6 1904.64    46.9 1901.81    69.7 1896.93    93.6 1893.02
     129 1890.28   152.6  1890.2   196.8 1888.42   200.9 1887.91  207.51 1885.31
   213.1 1884.28   218.4 1885.32   225.3 1887.62   229.4 1888.06   298.6 1888.16
   323.1 1888.77   343.4  1890.4   363.8 1891.22   441.1 1890.48   457.4 1891.98
   476.1 1891.89   487.7 1892.56     514 1895.24   589.6 1897.93   634.9 1905.53
     649 1909.28   660.4 1911.19   671.7 1915.45   688.7 1917.59   715.7 1924.43
#Mann= 6 ,-1,0
       0      .1       0     100     .06       0  207.51    .045       0
   218.4     .07       0  311.81     .05       0  566.65      .1       0
Bank Sta=207.51,218.4
XS Rating Curve= 0 ,0
Exp/Cntr(USF)=0,0
Exp/Cntr=0.3,0.1

Type RM Length L Ch R = 1 ,123     ,43.4,43.8,44.2
XS GIS Cut Line= 4
2185824.72148092 639642.373935872185930.67200965639456.786147535
2185875.32374591639170.257749055 2185692.5463487 638986.73535292
#Sta/Elev= 30
       0 1908.96      29 1901.43    55.4 1897.42   116.5 1895.38     158 1889.84
   176.4 1889.75   222.3 1887.85   233.7 1886.25241.59941883.949   245.9 1883.06
   249.6 1883.05 255.7891883.975   266.3 1887.77   278.5 1889.36     307 1890.56
   343.7 1890.66   433.3 1891.47     470 1890.65   538.3 1892.25   555.3 1891.85
   583.7 1894.51   625.6 1895.78   657.4 1898.64   674.4 1898.76   685.7 1900.35
     699 1903.17   727.2 1910.85   737.6 1914.25   753.7 1916.85   764.5  1919.3
#Mann= 6 ,-1,0
       0      .1       0      80     .06       0241.5994    .045       0
 255.789     .07       0   343.7     .05       0  665.53      .1       0
Bank Sta=241.5994,255.789
XS Rating Curve= 0 ,0
Exp/Cntr(USF)=0,0
Exp/Cntr=0.3,0.1

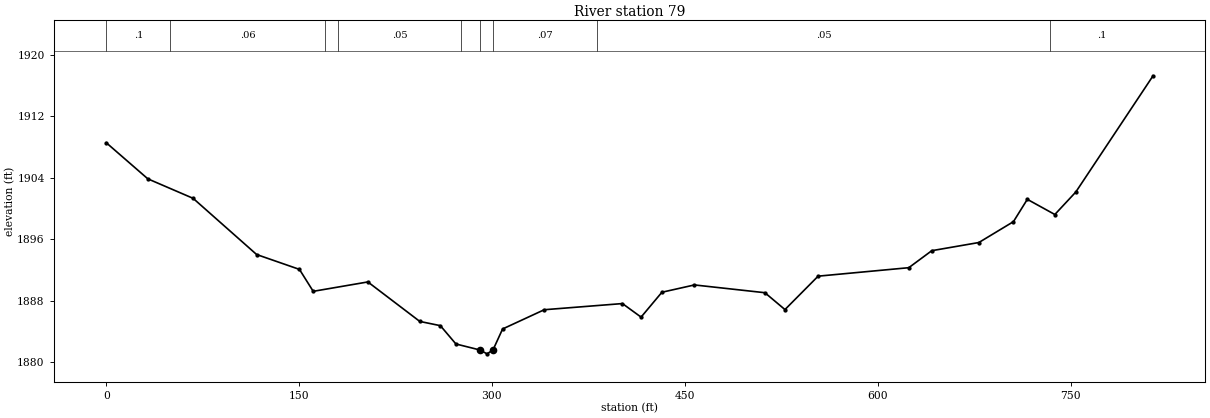
Type RM Length L Ch R = 1 ,79      ,,,
XS GIS Cut Line= 5
2185855.18731987639657.3981828442185978.98205516639518.444908544
2185957.83950344639344.0364855382185909.73879794639199.295051269
2185708.96536716638976.489000855
#Sta/Elev= 30
       0 1908.55    32.4 1903.85    67.6 1901.32     117 1894.02   150.3 1892.09
     161 1889.24   203.5 1890.46   243.9 1885.33   259.9 1884.78     272  1882.4
  290.67 1881.62   296.2 1881.12300.82631881.623   308.3 1884.35   340.7 1886.85
   401.5 1887.65     416 1885.89   432.2 1889.12   457.5 1890.07   512.3 1889.06
   527.9 1886.87   553.7 1891.21   624.2 1892.31   642.1 1894.52   678.7 1895.58
   705.6 1898.29   716.4 1901.19   737.8 1899.22   754.1 1902.14   814.2 1917.24
#Mann= 9 ,-1,0
       0      .1       0      50     .06       0     170      .1       0
     180     .05       0   276.1     .07       0  290.67    .045       0
300.8263     .07       0  381.79     .05       0  734.31      .1       0
Bank Sta=290.67,300.8263
XS Rating Curve= 0 ,0
Exp/Cntr(USF)=0,0
Exp/Cntr=0.3,0.1
LCMann Table=0

Chan Stop Cuts=-1
Use User Specified Reach Order=0
Composite Channel Slope=5